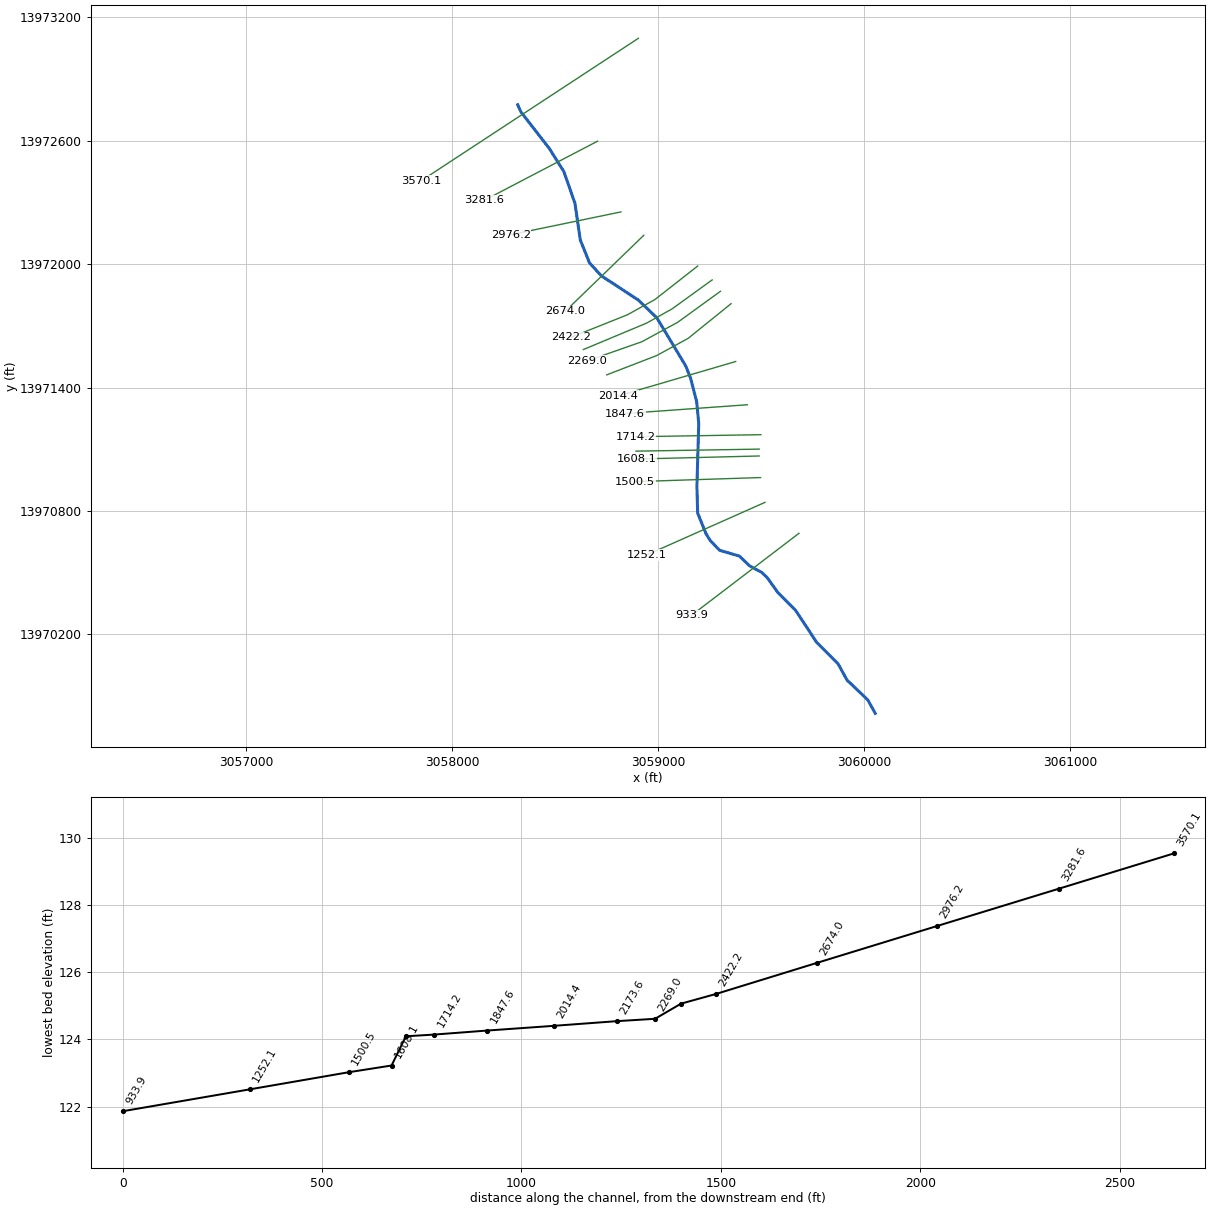
--- M109-01-00.PRJ (project) ---

Proj Title=M109-01-00
Current Plan=p03
Default Exp/Contr=.3,.1
English Units
Geom File=g01
Flow File=f02
Flow File=f03
Plan File=p02
Plan File=p03
Y Axis Title=Elevation
X Axis Title(PF)=Main Channel Distance
X Axis Title(XS)=Station
BEGIN DESCRIPTION:
Willow Creek
Metzler Creek
HCFCD Unit M109-01-00
Flood Hazard Model
10, 2, 1, 0.2% Event
Filename M102-00-00.prj
Prepared by: Halff Associates, Inc. Date: 03/05/2004
Reviewed by:                  Date:
STATUS Final RAS
END DESCRIPTION:
DSS File=dss
DSS Export Rating Curves= 0
DSS Export Rating Curve Sorted= 0
DSS Export Volume Flow Curves= 0
DXF OffsetX= 0
DXF OffsetY= 0
DXF ScaleX= 1
DXF ScaleY= 10

--- M109-01-00.p03 (plan) ---

Plan Title=Floodway
Program Version=3.11
Short Identifier=Floodway0607
Geom File=g01
Flow File=f03
Subcritical Flow
K Sum by GR= 0
Std Step Tol= 0.01
Critical Tol= 0.01
Num of Std Step Trials= 20
Max Error Tol= 0.3
Flow Tol Ratio= 0.001
Split Flow NTrial= 30
Split Flow Tol= 0.02
Split Flow Ratio= 0.02
Log Output Level= 0
Friction Slope Method= 1
Unsteady Friction Slope Method= 2
Unsteady Bridges Friction Slope Method= 1
Parabolic Critical Depth
Global Vel Dist= 0 , 0 , 0
Global Log Level= 0
CheckData=True
Encroach Param=-1 ,0,0, 2
Encroach River=M109-01-00
Encroach Reach=M109-01-00_0004
Encroach Node=3570.1
       1    4955    5036
Encroach Node=3281.6
       1    4955    5036
Encroach Node=2976.2
       1    4955    5036
Encroach Node=2674.0
       1 4963.95 5038.55
Encroach Node=2422.2
       1  4968.5  5034.2
Encroach Node=2334.0
       1  4969.2    5035
Encroach Node=2301.5
       1  4969.2    5035
Encroach Node=2269.0
       1  4969.2    5035
Encroach Node=2173.6
       1  4968.5  5034.2
Encroach Node=2014.4
       1 4966.25 5031.95
Encroach Node=1847.6
       1 4966.25 5031.95
Encroach Node=1714.2
       1 4964.45 5035.55
Encroach Node=1644.1
       1  4966.3  5037.4
Encroach Node=1626.1
       1  4966.3  5037.4
Encroach Node=1608.1
       1  4966.3  5037.4
Encroach Node=1500.5
       1 4964.45 5035.55
Encroach Node=1252.1
       1 4964.45 5035.55
Encroach Node=933.9
       1 4952.95 5047.05
Encroach Node=645.2
       1 4952.95 5047.05
Encroach Node=549.8
       1  4950.3  5044.4
Encroach Node=522.8
       1  4950.3  5044.4
Encroach Node=495.8
       1  4950.3  5044.4
Encroach Node=405.0
       1 4952.95 5047.05
Computation Interval=1HOUR
Output Interval=1HOUR
Run HTab= 0
Run UNet= 0
Run PostProcess= 0
UNET Theta= 1
UNET Theta Warmup= 1
UNET ZTol= 0.02
UNET ZSATol= 0.1
UNET MxIter= 20
UNET MaxInSteps= 20
UNET DtIC= 0
UNET DtMin= 0
UNET MaxCRTS= 20
UNET WFStab= 2
UNET SFStab= 1
UNET WFX= 1
UNET SFX= 1
UNET DSS MLevel= 4
UNET DZMax Abort= 100
UNET Convert EG Bridges=-1
UNET Use Existing IB Tables=-1
UNET Froude Reduction=False
UNET Froude Limit= 1
UNET Froude Power= 10
Instantaneous Interval=1HOUR
Write IC File= 0
Echo Input=False
Echo Output=False
Write Detailed= 0
Detailed Automatic Start=False, 10

--- M109-01-00.p02 (plan) ---

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Plan Title=FEMA Effective June 2007
Program Version=3.13
Short Identifier=FEMAeff0607
Geom File=g01
Flow File=f02
Encroach Param=-1 ,0,0, 0
DSS File=dss

--- M109-01-00.f03 (steady flow) ---

Flow Title=Floodway
Program Version=3.13
Number of Profiles= 2
Profile Names=1PCT_100yr,1PCTFloodway_100yrFW
River Rch & RM=M109-01-00,M109-01-00_0004       ,3570.1
    1080    1080
River Rch & RM=M109-01-00,M109-01-00_0004       ,2422.2
    1200    1200
River Rch & RM=M109-01-00,M109-01-00_0004       ,1500.5
    1240    1240
Boundary for River Rch & Prof#=M109-01-00,M109-01-00_0004       , 1
Up Type= 0
Dn Type= 3
Dn Slope=0.00238
Boundary for River Rch & Prof#=M109-01-00,M109-01-00_0004       , 2
Up Type= 0
Dn Type= 1
Dn Known WS=130.78
DSS Import GetInterval= 0
DSS Import GetPeak= 0
DSS Import FillOption= 0

--- M109-01-00.f02 (steady flow) ---

Flow Title=FEMA Effective June 2007
Program Version=3.13
Number of Profiles= 4
Profile Names=10PCT_10yr, 2PCT_50yr, 1PCT_100yr, 0.2PCT_500yr
River Rch & RM=M109-01-00,M109-01-00_0004 ,3570.1
     560     910    1080    1610
River Rch & RM=M109-01-00,M109-01-00_0004 ,2422.2
     600     990    1200    1700
River Rch & RM=M109-01-00,M109-01-00_0004 ,1500.5
     671    1058    1240    1807
Boundary for River Rch & Prof#=M109-01-00,M109-01-00_0004 , 1
Up Type= 0
Dn Type= 3
Dn Slope=0.00238
Boundary for River Rch & Prof#=M109-01-00,M109-01-00_0004 , 2
Up Type= 0
Dn Type= 3
Dn Slope=0.00238
Boundary for River Rch & Prof#=M109-01-00,M109-01-00_0004 , 3
Up Type= 0
Dn Type= 3
Dn Slope=0.00238
Boundary for River Rch & Prof#=M109-01-00,M109-01-00_0004 , 4
Up Type= 0
Dn Type= 3
Dn Slope=0.00238
DSS Import GetInterval= 0
DSS Import GetPeak= 0
DSS Import FillOption= 0

--- M109-01-00.g01 (geometry) ---

Geom Title=M109-01-00 June 2007
Program Version=3.13

River Reach=M109-01-00      ,M109-01-00_0004
Reach XY= 30
      3058318.11     13972774.97      3058333.61     13972740.62
      3058471.33     13972562.73      3058542.25       13972450.
      3058595.89     13972296.23      3058621.93     13972117.41
      3058666.64     13972005.87      3058723.93     13971943.37
      3058903.18     13971825.75        3058993.     13971739.61
      3059133.04     13971505.91      3059156.48     13971447.58
      3059186.69     13971330.91      3059196.58      13971225.7
      3059187.73     13970919.98      3059191.37     13970789.77
      3059231.48     13970690.29       3059251.5       13970657.
      3059298.14     13970608.52       3059394.5     13970580.39
      3059441.89     13970534.04      3059502.31     13970501.23
      3059528.35     13970476.23      3059579.39     13970404.87
        3059667.       13970316.      3059768.25       13970162.
      3059872.62     13970056.95      3059916.37     13969977.27
      3060016.54     13969881.75      3060053.13     13969815.79

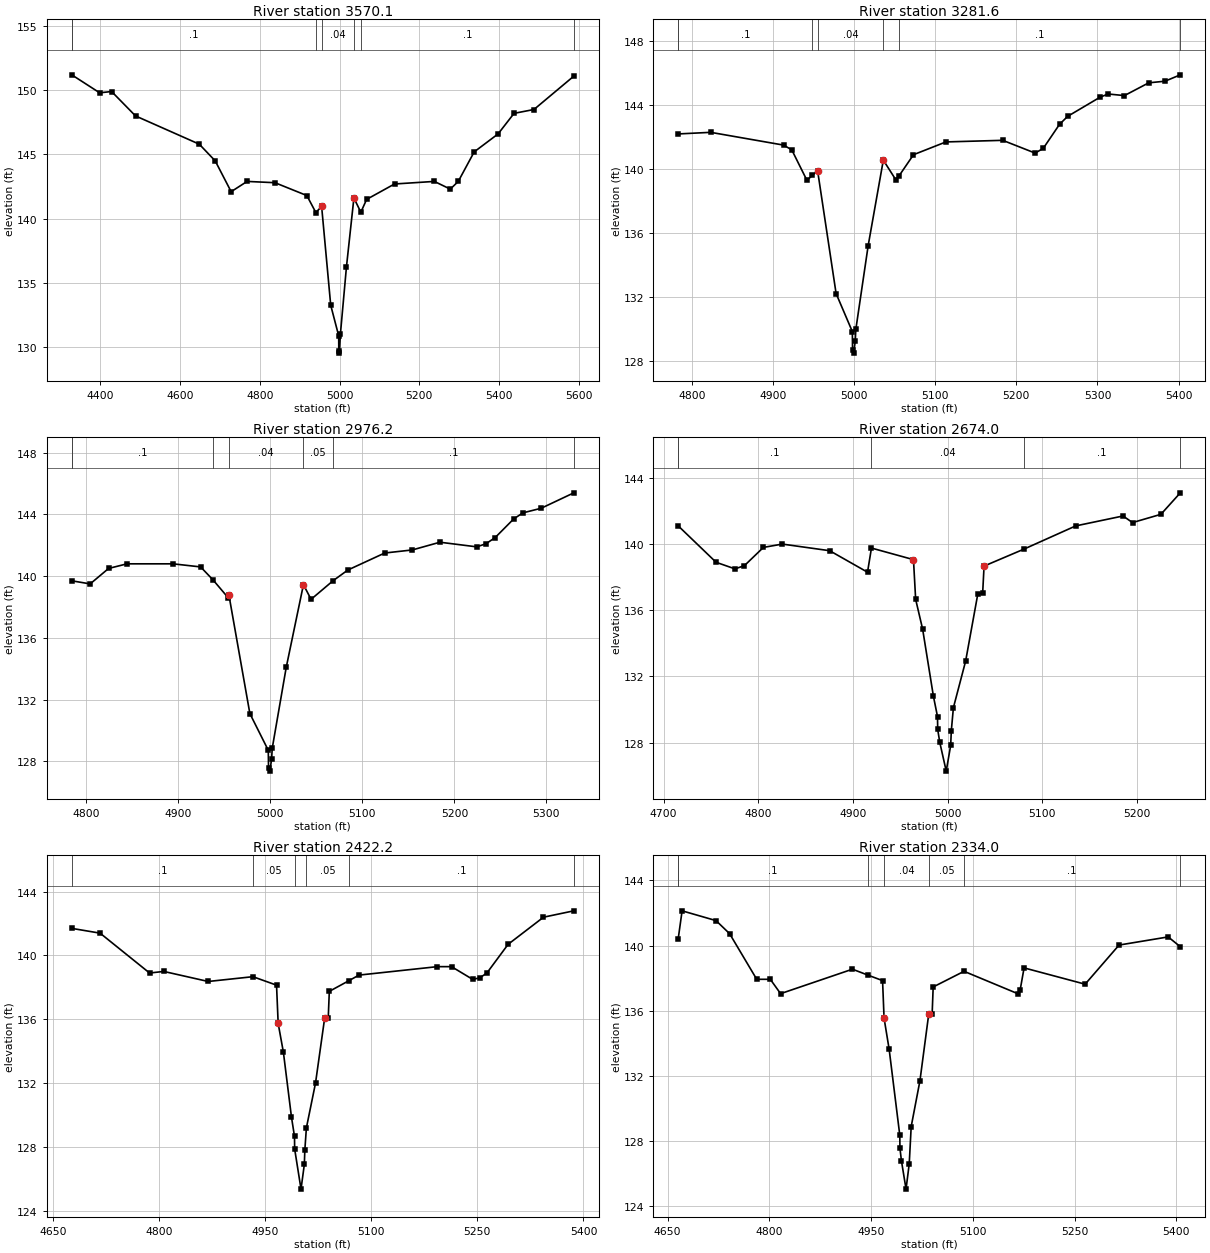
Type RM Length L Ch R = 1 ,3570.1  ,294.47,288.5,282.54
BEGIN DESCRIPTION:
Cross Section 3570.1
Cross Section XS07
END DESCRIPTION:
XS GIS Cut Line= 2
      3058903.53       13973098.      3057850.55      13972405.9
#Sta/Elev= 30
  4327.9   151.2  4397.9   149.8  4427.9   149.9  4487.9     148  4647.9   145.8
  4687.9   144.5  4727.9   142.1  4767.9   142.9  4837.9   142.8  4917.9   141.8
  4940.4  140.48    4955  140.95  4977.8  133.26  4997.8  130.88  4998.1  129.71
  4999.5  129.53  5002.1  131.01  5017.3  136.25    5036  141.61  5053.4   140.5
  5067.9   141.5  5137.9   142.7  5237.9   142.9  5277.9   142.3  5297.9   142.9
  5337.9   145.2  5397.9   146.6  5437.9   148.2  5487.9   148.5    5588   151.1
#Mann= 7 , 1 , 0
  4327.9      .2       0  4327.9      .1       0  4940.4     .05       0
    4955     .04       0    5036     .05       0  5053.4      .1       0
    5588      .2       0
Bank Sta=4955,5036
Exp/Cntr=0.3,0.1

Type RM Length L Ch R = 1 ,3281.6  ,322.1,305.4,288.72
BEGIN DESCRIPTION:
Cross Section XS-6.7
END DESCRIPTION:
XS GIS Cut Line= 2
      3058705.41      13972597.8      3058157.03      13972310.8
#Sta/Elev= 30
  4783.2   142.2  4823.2   142.3  4913.2   141.5  4923.2   141.2  4941.8   139.3
  4948.5   139.6    4955   139.9  4977.8  132.21  4997.8  129.83  4998.1  128.66
  4999.5  128.48  5001.4  129.25  5002.1  129.96  5017.3   135.2    5036  140.56
  5051.4  139.33  5054.9  139.54  5073.2   140.9  5113.2   141.7  5183.2   141.8
  5223.2     141  5233.2   141.3  5253.2   142.8  5263.2   143.3  5303.2   144.5
  5313.2   144.7  5333.2   144.6  5363.2   145.4  5383.2   145.5  5402.1   145.9
#Mann= 7 , 1 , 0
  4783.2      .2       0  4783.2      .1       0  4948.5     .05       0
    4955     .04       0    5036     .05       0  5054.9      .1       0
  5402.1      .2       0
Bank Sta=4955,5036
Exp/Cntr=0.3,0.1

Type RM Length L Ch R = 1 ,2976.2  ,268.3,302.2,336.15
BEGIN DESCRIPTION:
Cross Section XS-6.5
END DESCRIPTION:
XS GIS Cut Line= 2
      3058819.06       13972254.      3058284.89      13972143.2
#Sta/Elev= 30
  4784.3   139.7  4804.3   139.5  4824.3   140.5  4844.3   140.8  4894.3   140.8
  4924.3   140.6  4937.6  139.77  4954.3   138.6    4955  138.79  4977.8   131.1
  4997.8  128.72  4998.1  127.55  4999.5  127.37  5001.4  128.14  5002.1  128.85
  5017.3  134.09    5036  139.45  5044.3   138.5  5068.3  139.71  5084.3   140.4
  5124.3   141.5  5154.3   141.7  5184.3   142.2  5224.3   141.9  5234.3   142.1
  5244.3   142.5  5264.3   143.7  5274.3   144.1  5294.3   144.4  5329.8   145.4
#Mann= 7 , 1 , 0
  4784.3      .2       0  4784.3      .1       0  4937.6     .05       0
    4955     .04       0    5036     .05       0  5068.3      .1       0
  5329.8      .2       0
Bank Sta=4955,5036
Exp/Cntr=0.3,0.1

Type RM Length L Ch R = 1 ,2674.0  ,267.47,251.8,235.35
BEGIN DESCRIPTION:
Cross Section XS-6.2
END DESCRIPTION:
XS GIS Cut Line= 2
      3058929.87      13972140.3      3058549.13       13971771.
#Sta/Elev= 30
  4715.4   141.1  4755.4   138.9  4775.4   138.5  4785.4   138.7  4805.4   139.8
  4825.4     140  4875.4   139.6  4915.4   138.3 4919.55  139.76 4963.95  139.06
 4966.25  136.66 4973.65  134.85 4985.05  130.79 4989.35  129.57 4989.55  128.79
 4991.75  128.01 4998.55  126.27 5003.25  127.82 5003.95  128.72 5006.15  130.11
 5019.05  132.92 5031.95  136.99 5037.05  137.03 5038.55  138.67 5080.45  139.69
  5135.4   141.1  5185.4   141.7  5195.4   141.3  5225.4   141.8  5245.9   143.1
#Mann= 5 , 1 , 0
  4715.4      .2       0  4715.4      .1       0 4919.55     .04       0
 5080.45      .1       0  5245.9      .2       0
Bank Sta=4963.95,5038.55
Exp/Cntr=0.3,0.1

Type RM Length L Ch R = 1 ,2422.2  ,76.2,88.2,75.74
BEGIN DESCRIPTION:
Cross Section 2422.2
Cross Section XS06-Bridge3-con
END DESCRIPTION:
XS GIS Cut Line= 4
      3059191.64       13971991.      3058984.01      13971827.9
      3058850.53      13971753.8      3058578.63       13971645.
#Sta/Elev= 30
  4676.8   141.7  4716.8   141.4  4786.8   138.9  4806.8     139  4869.6  138.37
  4932.8  138.67  4966.2  138.14  4968.5  135.74  4975.9  133.93  4987.3  129.87
  4991.6  128.65  4991.8  127.87  5000.8  125.35  5005.5   126.9  5006.2   127.8
  5008.4  129.19  5021.3     132  5034.2  136.07  5039.3  136.11  5040.8  137.75
  5068.5  138.42  5082.7  138.77  5193.5   139.3  5213.5   139.3  5243.5   138.5
  5253.5   138.6  5263.5   138.9  5293.5   140.7  5343.5   142.4  5386.4   142.8
#Mann= 6 ,-1 , 0
  4676.8      .1       0  4932.8     .05       0  4991.6     .04       0
  5008.4     .05       0  5068.5      .1       0  5386.4      .2       0
Bank Sta=4968.5,5034.2
Exp/Cntr=0.5,0.3

Type RM Length L Ch R = 1 ,2334.0  ,65,65,65
BEGIN DESCRIPTION:
Upstream Section of Bridge/Culvert/Weir
END DESCRIPTION:
XS GIS Cut Line= 4
      3059261.59      13971923.3      3059067.34      13971782.6
      3058943.75      13971713.4      3058637.25      13971584.9
#Sta/Elev= 30
  4665.8  140.43  4671.5  142.13  4721.5  141.53  4741.5  140.73  4781.5  137.93
  4801.5  137.93  4816.7  137.05  4922.6  138.55  4945.2  138.19    4967  137.85
  4969.2  135.55  4976.7  133.64  4992.4  128.36  4992.6  127.58  4994.8   126.8
  5001.6  125.06  5006.3  126.61  5009.2   128.9  5022.1  131.71    5035  135.78
  5040.1  135.82  5041.6  137.46  5087.1  138.42  5166.2  137.05  5169.7  137.25
  5175.6  138.63  5265.6  137.63  5315.6  140.03    5388  140.53  5405.9  139.93
#Mann= 7 , 1 , 0
  4665.8      .2       0  4665.8      .1       0  4945.2     .05       0
  4969.2     .04       0    5035     .05       0  5087.1      .1       0
  5405.9      .2       0
#XS Ineff= 2 , 0
       0  4959.2   137.2    5045       0   137.2
Permanent Ineff=
       F       F
Bank Sta=4969.2,5035
Exp/Cntr=0.5,0.3

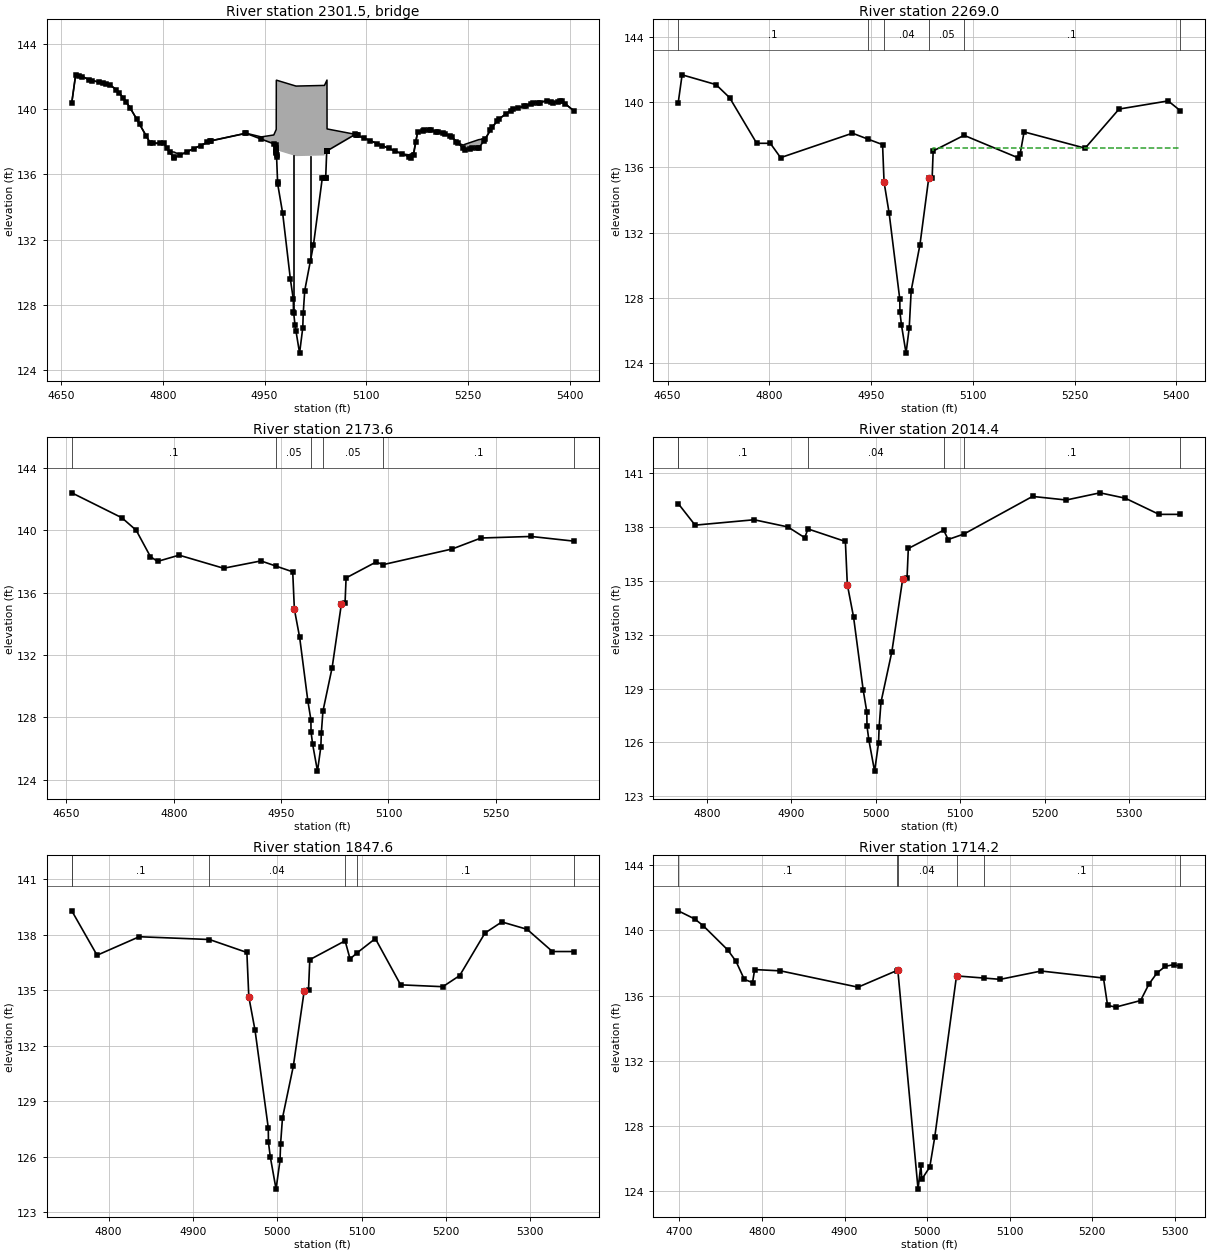
Type RM Length L Ch R = 3 ,2301.5  ,,,
BEGIN DESCRIPTION:
LONDON WAY DRIVE
Cross Section 2301.5
Structure ID: M109-01-00-03
END DESCRIPTION:
Bridge Culvert--1,0,-1,-1, 0
Deck Dist Width WeirC Skew NumUp NumDn MinLoCord MaxHiCord MaxSubmerge Is_Ogee
10,45,2.6,0, 51, 51, , , 0.95, 0, 1,1,,
  4665.8  4671.5  4681.5  4691.5  4721.5  4731.5  4741.5  4751.5  4781.5  4801.5
  4809.9  4816.7  4825.8  4870.4  4922.6  4945.2  4963.6    4967 4967.19  4967.3
  4967.5 4967.61  4967.7  4996.3  5038.3    5042 5042.11  5083.5  5152.9  5162.9
  5166.2  5169.7  5175.6  5185.6  5195.6  5215.6  5225.6  5235.6  5242.9  5245.6
  5265.6  5275.6  5285.6  5295.6  5315.6  5335.6  5345.6  5365.6  5375.6    5388
  5405.9
   140.4  142.11  142.01  141.81  141.51  141.21  140.71  140.11  137.94  137.91
   137.4  137.37   137.2  138.06  138.53   138.3  138.42  138.74  138.76  141.76
  141.78  141.78  141.78  141.42  141.46  141.79  138.79  138.46  137.26   137.2
  137.27  137.34  138.61  138.71  138.71  138.51  138.31  137.91   137.8  137.85
  138.13   138.2  138.91  139.41  140.01  140.21  140.41  140.51  140.41  140.51
   139.9
   140.4   142.1     142   141.8   141.5   141.2   140.7   140.1   137.9   137.9
  137.35  137.02  137.19  138.05  138.52  138.16  137.87  137.82  137.62  137.51
   137.3  137.18  137.48  137.12  137.16  137.49  137.49  138.45  137.25  137.08
  137.02  137.22   138.6   138.7   138.7   138.5   138.3   137.9  137.61   137.5
   137.6   138.2   138.9   139.4     140   140.2   140.4   140.5   140.4   140.5
   139.9
  4665.8  4671.5  4681.5  4691.5  4721.5  4731.5  4751.5  4781.5  4801.5  4809.9
  4816.7  4825.8  4870.4  4922.6  4945.2  4963.6    4967 4967.19  4967.3  4967.5
 4967.61  4967.7  4996.3  5038.3    5042 5042.11  5083.5  5152.9  5162.9  5166.2
  5169.7  5175.6  5195.6  5215.6  5225.6  5235.6  5242.9  5245.6  5255.6  5265.6
  5275.6  5285.6  5295.6  5315.6  5335.6  5345.6  5355.6  5365.6  5375.6    5388
  5405.9
   140.4  142.11  142.01  141.81  141.51  141.21  140.11  137.94  137.91   137.4
  137.37   137.2  138.06  138.53   138.3  138.42  138.74  138.76  141.76  141.78
  141.78  141.78  141.42  141.46  141.79  138.79  138.46  137.26   137.2  137.27
  137.34  138.61  138.71  138.51  138.31  137.91   137.8  137.85  138.03  138.13
   138.2  138.91  139.41  140.01  140.21  140.41  140.41  140.51  140.41  140.51
   139.9
  139.99  141.69  141.59  141.39  141.09  140.79  139.69  137.49  137.49  136.94
  136.61  136.78  137.64  138.11  137.75  137.46  137.41  137.21   137.1  136.89
  136.77  137.07  136.71  136.75  137.08  137.08  138.04  136.84  136.67  136.61
  136.81  138.19  138.29  138.09  137.89  137.49   137.2  137.09  137.19  137.19
  137.79  138.49  138.99  139.59  139.79  139.99  139.99  140.09  139.99  140.09
  139.49
Pier Skew, UpSta & Num, DnSta & Num=  ,4992.6, 2 ,4992.6, 2 , 0 , 0 , 0 ,,
     1.2     1.2
   126.4  138.17
     1.2     1.2
  125.99  137.76
Pier Skew, UpSta & Num, DnSta & Num=  ,5017.5, 2 ,5017.5, 2 , 0 , 0 , 0 ,,
     1.2     1.2
  129.54  138.14
     1.2     1.2
  129.13  137.73
Abutment Skew #Up #Dn= , 2 , 2
  4967.5  4969.3
  137.48  135.42
  4967.5  4969.3
  137.07  135.01
Abutment Skew #Up #Dn= , 2 , 2
  5040.1 5042.39
  135.79  137.49
  5040.1 5042.39
  135.38  137.08
BR Coef= 1 , 1 , 1 ,1.25, 0 ,,,0.8,0,2,0,
WSPro=,,,, 1 ,,,, 0 ,,,, 0 ,,,,-1 ,-1 ,-1 , 0 , 0 , 0 , 0 , 0
BR U #Sta/Elev= 128
  4665.8   140.4  4671.5   142.1  4675.8  142.06  4681.5     142  4691.5   141.8
  4695.8  141.76  4705.8  141.66  4711.5   141.6  4715.8  141.56  4721.5   141.5
  4731.5   141.2  4735.8  140.98  4741.5   140.7  4745.8  140.44  4751.5   140.1
  4761.5   139.4  4765.8  139.08  4775.8  138.33  4781.5   137.9  4785.8   137.9
  4795.8   137.9  4801.5   137.9  4805.8  137.62  4809.9  137.35  4815.8  137.06
  4816.7  137.02  4825.8  137.19  4835.8  137.39  4845.8  137.58  4855.8  137.77
  4865.8  137.96  4869.4  138.03  4870.4  138.05  4921.8  138.51  4922.6  138.52
  4945.2  138.16  4963.6  137.87    4967  137.82 4967.19  137.62  4967.3  137.51
 4967.41  137.39  4967.5   137.3 4967.61  137.18  4967.7  137.09  4969.2  135.52
  4969.3  135.42  4976.7  133.61  4988.1  129.55  4992.4  128.33  4992.6  127.55
    4993  127.48  4994.8  126.77  4996.3  126.39  5001.6  125.03  5006.3  126.58
    5007  127.48  5009.2  128.87  5017.5  130.67  5022.1  131.68    5035  135.75
  5038.3  135.78    5040  135.79  5040.1  135.79  5041.6  137.43 5041.89  137.44
    5042  137.44 5042.11  137.44 5042.19  137.44  5042.3  137.45  5042.4  137.45
  5083.5  138.45  5084.5  138.43    5086  138.41  5087.1  138.39    5096  138.23
    5106  138.06    5116  137.89  5122.9  137.77  5132.9   137.6  5142.9  137.42
  5152.9  137.25  5162.9  137.08  5166.2  137.02  5169.7  137.22  5172.9  137.97
  5175.6   138.6  5182.9  138.67  5185.6   138.7  5192.9   138.7  5195.6   138.7
  5202.9  138.63  5205.6   138.6  5212.9  138.53  5215.6   138.5  5222.9  138.35
  5225.6   138.3  5232.9  138.01  5235.6   137.9  5242.9  137.61  5245.6   137.5
  5252.9  137.57  5255.6   137.6  5262.9   137.6  5265.6   137.6  5272.9  138.04
  5275.6   138.2  5282.9  138.71  5285.6   138.9  5292.9  139.26  5295.6   139.4
  5305.6   139.7  5312.9  139.92  5315.6     140  5322.9  140.07  5332.9  140.17
  5335.6   140.2  5342.9  140.35  5345.6   140.4  5352.9   140.4  5355.6   140.4
  5365.6   140.5  5372.9  140.43  5375.6   140.4  5382.9  140.47  5385.6   140.5
    5388   140.5  5392.9  140.34  5405.9   139.9
BR U #Mann= 5
  4665.8      .1  4945.2     .05  4969.2     .03    5035     .05  5087.1      .1
BR U Banks=4969.2,5035
BR D #Sta/Elev= 128
  4665.8  139.99  4671.5  141.69  4675.8  141.65  4681.5  141.59  4691.5  141.39
  4695.8  141.35  4705.8  141.25  4711.5  141.19  4715.8  141.15  4721.5  141.09
  4731.5  140.79  4735.8  140.57  4741.5  140.29  4745.8  140.03  4751.5  139.69
  4761.5  138.99  4765.8  138.67  4775.8  137.92  4781.5  137.49  4785.8  137.49
  4795.8  137.49  4801.5  137.49  4805.8  137.21  4809.9  136.94  4815.8  136.65
  4816.7  136.61  4825.8  136.78  4835.8  136.98  4845.8  137.17  4855.8  137.36
  4865.8  137.55  4869.4  137.62  4870.4  137.64  4921.8   138.1  4922.6  138.11
  4945.2  137.75  4963.6  137.46    4967  137.41 4967.19  137.21  4967.3   137.1
 4967.41  136.98  4967.5  136.89 4967.61  136.77  4967.7  136.68  4969.2  135.11
  4969.3  135.01  4976.7   133.2  4988.1  129.14  4992.4  127.92  4992.6  127.14
    4993  127.07  4994.8  126.36  4996.3  125.98  5001.6  124.62  5006.3  126.17
    5007  127.07  5009.2  128.46  5017.5  130.26  5022.1  131.27    5035  135.34
  5038.3  135.37    5040  135.38  5040.1  135.38  5041.6  137.02 5041.89  137.03
    5042  137.03 5042.11  137.03 5042.19  137.03  5042.3  137.04  5042.4  137.04
  5083.5  138.04  5084.5  138.02    5086     138  5087.1  137.98    5096  137.82
    5106  137.65    5116  137.48  5122.9  137.36  5132.9  137.19  5142.9  137.01
  5152.9  136.84  5162.9  136.67  5166.2  136.61  5169.7  136.81  5172.9  137.56
  5175.6  138.19  5182.9  138.26  5185.6  138.29  5192.9  138.29  5195.6  138.29
  5202.9  138.22  5205.6  138.19  5212.9  138.12  5215.6  138.09  5222.9  137.94
  5225.6  137.89  5232.9   137.6  5235.6  137.49  5242.9   137.2  5245.6  137.09
  5252.9  137.16  5255.6  137.19  5262.9  137.19  5265.6  137.19  5272.9  137.63
  5275.6  137.79  5282.9   138.3  5285.6  138.49  5292.9  138.85  5295.6  138.99
  5305.6  139.29  5312.9  139.51  5315.6  139.59  5322.9  139.66  5332.9  139.76
  5335.6  139.79  5342.9  139.94  5345.6  139.99  5352.9  139.99  5355.6  139.99
  5365.6  140.09  5372.9  140.02  5375.6  139.99  5382.9  140.06  5385.6  140.09
    5388  140.09  5392.9  139.93  5405.9  139.49
BR D #Mann= 5
  4665.8      .1  4945.2     .05  4969.2     .03    5035     .05  5087.1      .1
BR D Banks=4969.2,5035
BC Design=,, 0 ,, 0 ,,,,,,
BC HTab HWMax=142.13

Type RM Length L Ch R = 1 ,2269.0  ,95.4,95.4,95.4
BEGIN DESCRIPTION:
Downstream Section of Bridge/Culvert/Weir
END DESCRIPTION:
XS GIS Cut Line= 4
      3059301.79      13971867.9      3059093.68      13971716.8
      3058920.65      13971622.8       3058653.7      13971528.9
#Sta/Elev= 30
  4665.8  139.98  4671.5  141.68  4721.5  141.08  4741.5  140.28  4781.5  137.48
  4801.5  137.48  4816.7   136.6  4922.6   138.1  4945.2  137.74    4967   137.4
  4969.2   135.1  4976.7  133.19  4992.4  127.91  4992.6  127.13  4994.8  126.35
  5001.6  124.61  5006.3  126.16  5009.2  128.45  5022.1  131.26    5035  135.33
  5040.1  135.37  5041.6  137.01  5087.1  137.97  5166.2   136.6  5169.7   136.8
  5175.6  138.18  5265.6  137.18  5315.6  139.58    5388  140.08  5405.9  139.48
#Mann= 6 ,-1 , 0
  4665.8      .1       0  4945.2     .05       0  4969.2     .04       0
    5035     .05       0  5087.1      .1       0  5405.9      .2       0
#XS Ineff= 2 , 0
       0 4962.53   137.2 5041.67       0   137.2
Permanent Ineff=
       F       F
Bank Sta=4969.2,5035
Exp/Cntr=0.5,0.3

Type RM Length L Ch R = 1 ,2173.6  ,173.07,159.2,147.09
BEGIN DESCRIPTION:
Cross Section 2173.6
Cross Section XS05-Bridge3-exp
END DESCRIPTION:
XS GIS Cut Line= 4
       3059353.4      13971807.7      3059145.77      13971639.6
      3058992.52      13971555.6      3058750.28      13971461.7
#Sta/Elev= 30
  4657.4   142.4  4727.4   140.8  4747.4     140  4767.4   138.3  4777.4     138
  4807.4   138.4  4869.6  137.56  4921.8  138.03  4943.3  137.69  4966.2  137.33
  4968.5  134.93  4975.9  133.12  4987.3  129.06  4991.6  127.84  4991.8  127.06
    4994  126.28  5000.8  124.54  5005.5  126.09  5006.2  126.99  5008.4  128.38
  5021.3  131.19  5034.2  135.26  5039.3   135.3  5040.8  136.94  5082.7  137.96
  5092.4  137.79  5189.3   138.8  5229.3   139.5  5299.3   139.6  5359.1   139.3
#Mann= 6 ,-1 , 0
  4657.4      .1       0  4943.3     .05       0  4991.6     .04       0
  5008.4     .05       0  5092.4      .1       0  5359.1      .2       0
Bank Sta=4968.5,5034.2
Exp/Cntr=0.3,0.1

Type RM Length L Ch R = 1 ,2014.4  ,179.63,166.8,153.97
BEGIN DESCRIPTION:
Cross Section XS-4.7
END DESCRIPTION:
XS GIS Cut Line= 2
      3059375.96      13971526.6      3058804.85       13971359.
#Sta/Elev= 30
  4765.8   139.3  4785.8   138.1  4855.8   138.4  4895.8     138  4915.8   137.4
 4919.55  137.89 4963.95  137.19 4966.25  134.79 4973.65  132.98 4985.05  128.92
 4989.35   127.7 4989.55  126.92 4991.75  126.14 4998.55   124.4 5003.25  125.95
 5003.95  126.85 5006.15  128.24 5019.05  131.05 5031.95  135.12 5037.05  135.16
 5038.55   136.8 5080.45  137.82  5085.8   137.3  5104.7  137.61  5185.8   139.7
  5225.8   139.5  5265.8   139.9  5295.8   139.6  5335.8   138.7    5361   138.7
#Mann= 6 , 1 , 0
  4765.8      .2       0  4765.8      .1       0 4919.55     .04       0
 5080.45     .05       0  5104.7      .1       0    5361      .2       0
Bank Sta=4966.25,5031.95
Exp/Cntr=0.3,0.1

Type RM Length L Ch R = 1 ,1847.6  ,136.64,133.4,129.99
BEGIN DESCRIPTION:
Cross Section XS-4.3
END DESCRIPTION:
XS GIS Cut Line= 2
      3059432.79      13971316.4      3058838.95      13971273.7
#Sta/Elev= 30
  4756.3   139.3  4786.3   136.9  4836.3   137.9 4919.55  137.75 4963.95  137.05
 4966.25  134.65 4973.65  132.84 4989.35  127.56 4989.55  126.78 4991.75     126
 4998.55  124.26 5003.25  125.81 5003.95  126.71 5006.15   128.1 5019.05  130.91
 5031.95  134.98 5037.05  135.02 5038.55  136.66 5080.45  137.68  5086.3   136.7
  5094.4  137.02  5116.3   137.8  5146.3   135.3  5196.3   135.2  5216.3   135.8
  5246.3   138.1  5266.3   138.7  5296.3   138.3  5326.3   137.1  5351.7   137.1
#Mann= 6 , 1 , 0
  4756.3      .2       0  4756.3      .1       0 4919.55     .04       0
 5080.45     .05       0  5094.4      .1       0  5351.7      .2       0
Bank Sta=4966.25,5031.95
Exp/Cntr=0.3,0.1

Type RM Length L Ch R = 1 ,1714.2  ,70.1,70.1,70.1
BEGIN DESCRIPTION:
Cross Section 1714.2
Cross Section XS04-Bridge2-con
END DESCRIPTION:
XS GIS Cut Line= 2
      3059497.98      13971170.8      3058889.92      13971160.9
#Sta/Elev= 30
  4698.5   141.2  4718.5   140.7  4728.5   140.3  4758.5   138.8  4768.5   138.1
  4778.5     137  4788.5   136.8 4791.05   137.6 4822.35  137.52 4916.25  136.52
  4963.3  137.54 4964.45  137.57 4988.95  124.14 4992.35  125.63 4993.55  124.75
 5003.15  125.49 5009.15  127.32 5035.55  137.21  5068.5  137.08 5088.45     137
 5138.05  137.51 5213.55  137.08  5218.5   135.4  5228.5   135.3  5258.5   135.7
  5268.5   136.7  5278.5   137.4  5288.5   137.8  5298.5   137.9  5306.6   137.8
#Mann= 6 ,-1 , 0
  4698.5      .1       0  4963.3     .05       0 4964.45     .04       0
 5035.55     .05       0  5068.5      .1       0  5306.6      .2       0
Bank Sta=4964.45,5035.55
Exp/Cntr=0.5,0.3

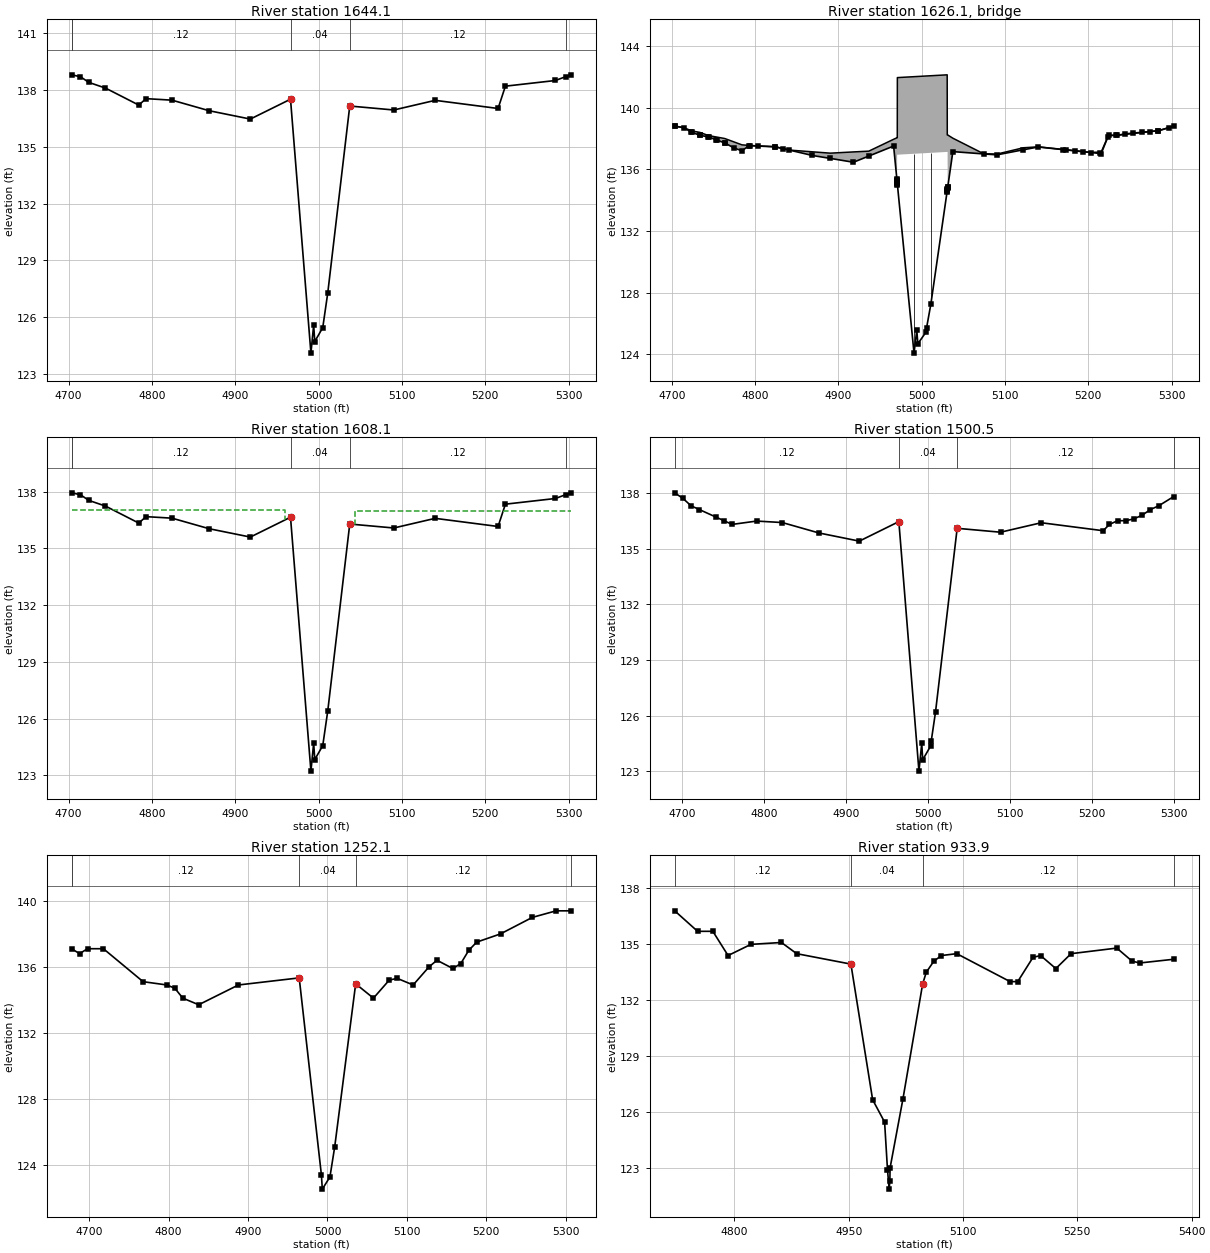
Type RM Length L Ch R = 1 ,1644.1  ,36,36,36
BEGIN DESCRIPTION:
Upstream Section of Bridge/Culvert/Weir
END DESCRIPTION:
XS GIS Cut Line= 2
      3059490.09      13971100.7      3058891.91      13971090.8
#Sta/Elev= 23
  4703.6  138.81  4714.2  138.71  4724.2  138.41  4744.2  138.11  4784.2  137.21
  4792.9  137.55  4824.1  137.47  4868.8  136.91  4918.1  136.47  4966.3  137.52
  4990.8  124.09  4994.1  125.58  4995.4   124.7    5005  125.44    5011  127.27
  5037.4  137.16  5090.3  136.95  5139.9  137.46  5215.4  137.03  5224.2  138.21
  5284.2  138.51    5297  138.72  5302.5  138.81
#Mann= 5 , 1 , 0
  4703.6      .2       0  4703.6     .12       0  4966.3     .04       0
  5037.4     .12       0    5297      .2       0
#XS Ineff= 2 , 0
       0  4956.3  137.05  5047.4       0  136.99
Permanent Ineff=
       F       F
Bank Sta=4966.3,5037.4
Exp/Cntr=0.5,0.3

Type RM Length L Ch R = 3 ,1626.1  ,,,
BEGIN DESCRIPTION:
PRIVATE ACCESS ROAD
ACCESS ROAD 2500FT US WILLOWICK
Cross Section 1626.1
Structure ID: M109-01-00-02
END DESCRIPTION:
Bridge Culvert--1,0,-1,-1, 0
Deck Dist Width WeirC Skew NumUp NumDn MinLoCord MaxHiCord MaxSubmerge Is_Ogee
10,16,2.6,0, 33, 33, , , 0.95, 0, 1,1,,
  4703.6  4714.2  4724.2  4733.6  4744.2  4763.6  4784.2  4792.9  4824.1  4841.2
  4890.3  4918.1  4936.5  4966.3 4970.43  4970.5 4970.69  4970.8  5030.6 5030.71
 5031.09  5031.2  5037.4  5074.4  5090.3  5122.1  5139.9  5203.6  5215.4  5224.2
  5234.2  5284.2  5302.5
   138.8  138.71  138.49   138.4  138.19     138  137.59  137.55  137.47  137.25
  137.05  137.13  137.18  137.95  138.05  138.05  138.05  141.95  142.13  138.23
  138.23  138.23  138.02  137.01  136.99   137.4  137.46   137.1  137.12  138.21
  138.21  138.51   138.8
   138.8   138.7   138.4  138.21   138.1  137.71   137.2  137.54  137.46  137.25
  136.71  136.46  136.86  137.51  135.25  136.95  136.95  136.95  137.13  137.13
  137.13  134.83  137.15     137  136.94  137.27  137.45  137.09  137.02   138.2
   138.2   138.5   138.8
  4703.6  4714.2  4724.2  4733.6  4744.2  4763.6  4784.2  4792.9  4824.1  4841.2
  4890.3  4918.1  4936.5  4966.3 4970.43  4970.5 4970.69  4970.8  5030.6 5030.71
 5031.09  5031.2  5037.4  5074.4  5090.3  5122.1  5139.9  5203.6  5215.4  5224.2
  5234.2  5284.2  5302.5
   138.8  138.71  138.49   138.4  138.19     138  137.59  137.55  137.47  137.25
  137.05  137.13  137.18  137.95  138.05  138.05  138.05  141.95  142.13  138.23
  138.23  138.23  138.02  137.01  136.99   137.4  137.46   137.1  137.12  138.21
  138.21  138.51   138.8
  137.96  137.86  137.56  137.37  137.26  136.87  136.36   136.7  136.62  136.41
  135.87  135.62  136.02  136.67  134.41  136.11  136.11  136.11  136.29  136.29
  136.29  133.99  136.31  136.16   136.1  136.43  136.61  136.25  136.18  137.36
  137.36  137.66  137.96
Pier Skew, UpSta & Num, DnSta & Num=  ,4990.8, 2 ,4990.8, 2 , 0 , 0 , 0 ,,
      .8      .8
  123.26  138.01
      .8      .8
  122.42  137.17
Pier Skew, UpSta & Num, DnSta & Num=  ,5011, 2 ,5011, 2 , 0 , 0 , 0 ,,
      .8      .8
  126.14  138.07
      .8      .8
   125.3  137.23
BR Coef= 1 , 1 , 1 ,1.25, 0 ,,,0.8,0,2,0,
WSPro=,,,, 1 ,,,, 0 ,,,, 0 ,,,,-1 ,-1 ,-1 , 0 , 0 , 0 , 0 , 0
BR U #Sta/Elev= 71
  4703.6   138.8  4704.2   138.8  4714.2   138.7  4723.6  138.42  4724.2   138.4
  4733.6  138.21  4734.2   138.2  4743.6  138.11  4744.2   138.1  4753.6  137.91
  4754.2   137.9  4763.6  137.71  4764.2   137.7  4774.2   137.4  4784.2   137.2
  4792.9  137.54  4793.6  137.54  4803.6  137.51  4823.6  137.46  4824.1  137.46
  4833.6  137.34  4841.2  137.25  4868.8   136.9  4890.3  136.71  4918.1  136.46
  4936.5  136.86  4966.3  137.51  4970.2  135.37 4970.31  135.31 4970.43  135.25
  4970.5  135.21 4970.69   135.1  4970.8  135.04 4970.91  134.98  4990.8  124.08
  4994.1  125.57  4995.4  124.69    5005  125.43  5005.8   125.7    5011  127.26
 5030.49  134.56  5030.6   134.6 5030.71  134.64 5030.97  134.74 5031.09  134.79
  5031.2  134.83  5031.3  134.86  5037.4  137.15  5074.4     137  5090.3  136.94
  5122.1  137.27  5139.9  137.45  5169.4  137.28  5173.6  137.26  5183.6   137.2
  5193.6  137.14  5203.6  137.09  5213.6  137.03  5215.4  137.02  5223.6  138.12
  5224.2   138.2  5233.6   138.2  5234.2   138.2  5244.2   138.3  5253.6  138.35
  5264.2   138.4  5273.6  138.45  5283.6   138.5  5284.2   138.5    5297  138.71
  5302.5   138.8
BR U #Mann= 4
  4703.6     .12  4966.3     .03  5037.4     .12    5297      .2
BR U Banks=4966.3,5037.4
BR D #Sta/Elev= 71
  4703.6  137.96  4704.2  137.96  4714.2  137.86  4723.6  137.58  4724.2  137.56
  4733.6  137.37  4734.2  137.36  4743.6  137.27  4744.2  137.26  4753.6  137.07
  4754.2  137.06  4763.6  136.87  4764.2  136.86  4774.2  136.56  4784.2  136.36
  4792.9   136.7  4793.6   136.7  4803.6  136.67  4823.6  136.62  4824.1  136.62
  4833.6   136.5  4841.2  136.41  4868.8  136.06  4890.3  135.87  4918.1  135.62
  4936.5  136.02  4966.3  136.67  4970.2  134.53 4970.31  134.47 4970.43  134.41
  4970.5  134.37 4970.69  134.26  4970.8   134.2 4970.91  134.14  4990.8  123.24
  4994.1  124.73  4995.4  123.85    5005  124.59  5005.8  124.86    5011  126.42
 5030.49  133.72  5030.6  133.76 5030.71   133.8 5030.97   133.9 5031.09  133.95
  5031.2  133.99  5031.3  134.02  5037.4  136.31  5074.4  136.16  5090.3   136.1
  5122.1  136.43  5139.9  136.61  5169.4  136.44  5173.6  136.42  5183.6  136.36
  5193.6   136.3  5203.6  136.25  5213.6  136.19  5215.4  136.18  5223.6  137.28
  5224.2  137.36  5233.6  137.36  5234.2  137.36  5244.2  137.46  5253.6  137.51
  5264.2  137.56  5273.6  137.61  5283.6  137.66  5284.2  137.66    5297  137.87
  5302.5  137.96
BR D #Mann= 4
  4703.6     .12  4966.3     .03  5037.4     .12    5297      .2
BR D Banks=4966.3,5037.4
BC Design=,, 0 ,, 0 ,,,,,,
BC HTab HWMax=138.81

Type RM Length L Ch R = 1 ,1608.1  ,107.6,107.6,107.6
BEGIN DESCRIPTION:
Downstream Section of Bridge/Culvert/Weir
END DESCRIPTION:
XS GIS Cut Line= 2
      3059489.93      13971067.3       3058896.7      13971052.5
#Sta/Elev= 23
  4703.6  137.94  4714.2  137.84  4724.2  137.54  4744.2  137.24  4784.2  136.34
  4792.9  136.68  4824.1   136.6  4868.8  136.04  4918.1   135.6  4966.3  136.65
  4990.8  123.22  4994.1  124.71  4995.4  123.83    5005  124.57    5011   126.4
  5037.4  136.29  5090.3  136.08  5139.9  136.59  5215.4  136.16  5224.2  137.34
  5284.2  137.64    5297  137.85  5302.5  137.94
#Mann= 5 , 1 , 0
  4703.6      .2       0  4703.6     .12       0  4966.3     .04       0
  5037.4     .12       0    5297      .2       0
#XS Ineff= 2 , 0
       0 4959.63  137.05 5044.07       0  136.99
Permanent Ineff=
       F       F
Bank Sta=4966.3,5037.4
Exp/Cntr=0.5,0.3

Type RM Length L Ch R = 1 ,1500.5  ,224.95,248.4,271.91
BEGIN DESCRIPTION:
Cross Section 1500.5
Cross Section XS03-Bridge2-exp
END DESCRIPTION:
XS GIS Cut Line= 2
      3059496.76      13970962.4       3058888.7      13970942.6
#Sta/Elev= 30
  4691.2     138  4701.2   137.7  4711.2   137.3  4721.2   137.1  4741.2   136.7
  4751.2   136.5  4761.2   136.3 4791.05  136.48 4822.35   136.4 4866.95  135.84
 4916.25   135.4 4964.45  136.45 4988.95  123.02 4992.35  124.51 4993.55  123.63
 5003.15  124.37 5003.95  124.64 5009.15   126.2 5035.55  136.09 5088.45  135.88
 5138.05  136.39 5213.55  135.96  5221.2   136.3  5231.2   136.5  5241.2   136.5
  5251.2   136.6  5261.2   136.8  5271.2   137.1  5281.2   137.3  5299.6   137.8
#Mann= 4 ,-1 , 0
  4691.2     .12       0 4964.45     .04       0 5035.55     .12       0
  5299.6      .2       0
Bank Sta=4964.45,5035.55
Exp/Cntr=0.3,0.1

Type RM Length L Ch R = 1 ,1252.1  ,297.14,318.2,322.56
BEGIN DESCRIPTION:
Cross Section XS-2.5
END DESCRIPTION:
XS GIS Cut Line= 2
      3059518.03      13970841.8      3058944.08      13970586.1
#Sta/Elev= 30
  4677.9   137.1  4687.9   136.8  4697.9   137.1  4717.9   137.1  4767.9   135.1
  4797.9   134.9  4807.9   134.7  4817.9   134.1  4837.9   133.7  4887.9   134.9
 4964.45  135.33 4992.35  123.39 4993.55  122.51 5003.15  123.25 5009.15  125.08
 5035.55  134.97  5057.9   134.1  5077.9   135.2  5087.9   135.3  5107.9   134.9
  5127.9     136  5137.9   136.4  5157.9   135.9  5167.9   136.2  5177.9     137
  5187.9   137.5  5217.9     138  5257.9     139  5287.9   139.4  5306.2   139.4
#Mann= 5 , 1 , 0
  4677.9      .2       0  4677.9     .12       0 4964.45     .04       0
 5035.55     .12       0  5306.2      .2       0
Bank Sta=4964.45,5035.55
Exp/Cntr=0.3,0.1

Type RM Length L Ch R = 1 ,933.9   ,286.68,288.7,282.72
BEGIN DESCRIPTION:
Cross Section XS-2.2
END DESCRIPTION:
XS GIS Cut Line= 2
      3059682.82      13970691.3      3059162.86      13970293.5
#Sta/Elev= 30
  4721.8   136.8  4751.8   135.7  4771.8   135.7  4791.8   134.4  4821.8     135
  4861.8   135.1  4881.8   134.5 4952.95  133.94 4981.45  126.66 4997.15  125.46
 5000.95   122.9 5003.15  121.86 5004.05  122.32 5004.35     123 5021.25  126.71
 5047.05  132.87  5051.8   133.5  5061.8   134.1  5071.8   134.4  5091.8   134.5
  5161.8     133  5171.8     133  5191.8   134.3  5201.8   134.4  5221.8   133.7
  5241.8   134.5  5301.8   134.8  5321.8   134.1  5331.8     134  5376.5   134.2
#Mann= 4 ,-1 , 0
  4721.8     .12       0 4952.95     .04       0 5047.05     .12       0
  5376.5      .2       0
Bank Sta=4952.95,5047.05
Exp/Cntr=0.3,0.1