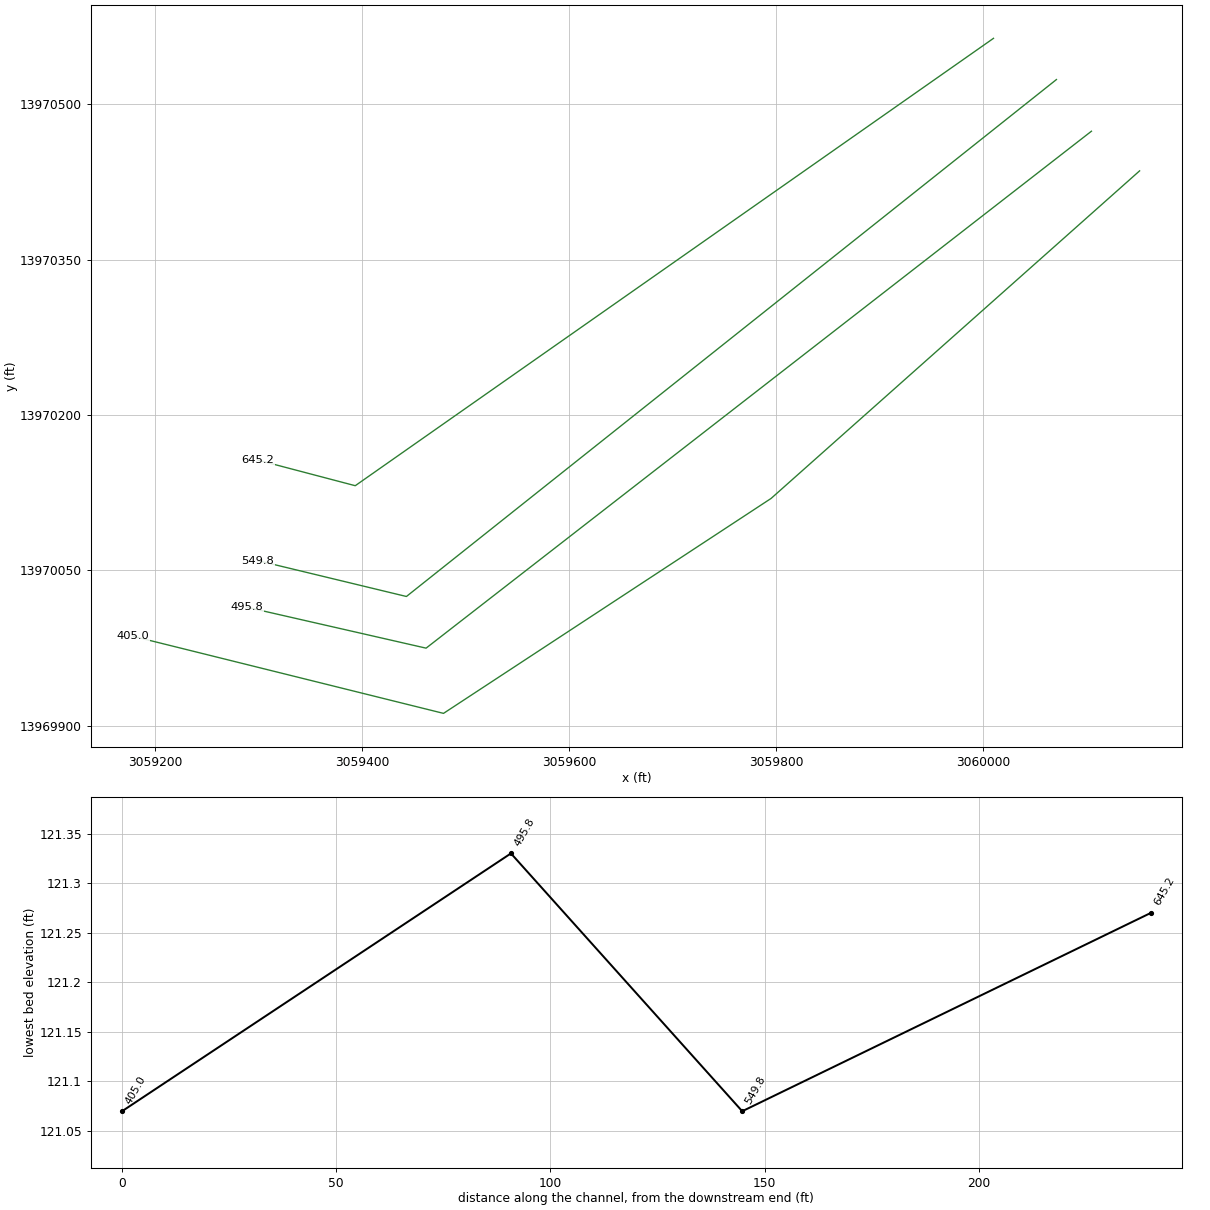
HEC-RAS study M109-01-00.PRJ: M109-01-00

--- M109-01-00.g01 (geometry) --- (continued)

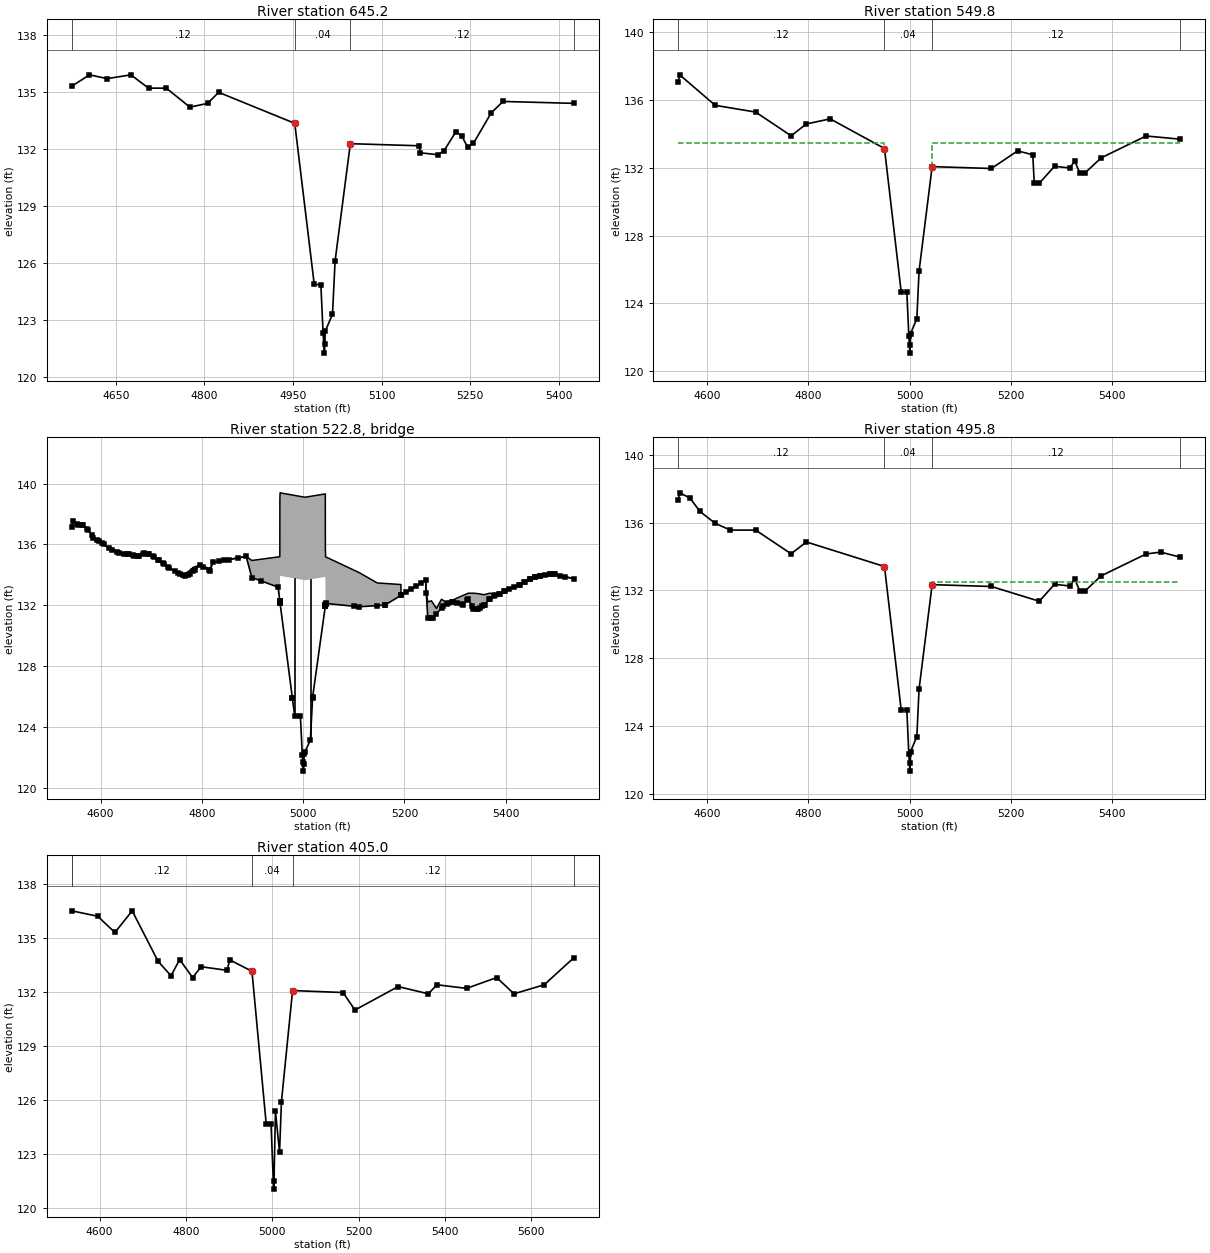
Type RM Length L Ch R = 1 ,645.2   ,95.4,95.4,95.4
BEGIN DESCRIPTION:
Cross Section 645.6
Cross Section XS02-Bridge1-con
END DESCRIPTION:
XS GIS Cut Line= 3
      3060010.06      13970563.8       3059393.6      13970131.7
      3059299.67      13970156.4
#Sta/Elev= 30
  4575.5   135.3  4605.5   135.9  4635.5   135.7  4675.5   135.9  4705.5   135.2
  4735.5   135.2  4775.5   134.2  4805.5   134.4 4824.15  134.98 4952.95  133.35
 4985.95  124.88 4997.15  124.87 5000.95  122.31 5003.15  121.27 5004.05  121.73
 5004.35  122.41 5016.85  123.31 5021.25  126.12 5047.05  132.28 5163.95  132.17
  5165.5   131.8  5195.5   131.7  5205.5   131.9  5225.5   132.9  5235.5   132.7
  5245.5   132.1  5255.5   132.3  5285.5   133.9  5305.5   134.5  5425.4   134.4
#Mann= 4 ,-1 , 0
  4575.5     .12       0 4952.95     .04       0 5047.05     .12       0
  5425.4      .2       0
Bank Sta=4952.95,5047.05
Exp/Cntr=0.5,0.3

Type RM Length L Ch R = 1 ,549.8   ,54,54,54
BEGIN DESCRIPTION:
Upstream Section of Bridge/Culvert/Weir
END DESCRIPTION:
XS GIS Cut Line= 3
      3060070.86       13970524.      3059443.02      13970024.7
      3059299.66      13970059.3
#Sta/Elev= 30
  4543.1   137.1    4546   137.5    4616   135.7    4696   135.3    4766   133.9
    4796   134.6  4843.1   134.9  4950.3  133.15  4983.3  124.68  4994.5  124.67
  4998.3  122.11  5000.5  121.07  5001.4  121.53  5001.7  122.21  5014.2  123.11
  5018.6  125.92  5044.4  132.08  5161.4  131.97  5213.1  133.01  5243.1  132.78
    5246   131.1    5256   131.1    5286   132.1    5316     132    5326   132.4
    5336   131.7    5346   131.7  5378.2   132.6  5466.9  133.89  5534.4   133.7
#Mann= 4 ,-1 , 0
  4543.1     .12       0  4950.3     .04       0  5044.4     .12       0
  5534.4      .2       0
#XS Ineff= 2 , 0
       0  4950.3   133.5  5044.4       0   133.5
Permanent Ineff=
       F       F
Bank Sta=4950.3,5044.4
Exp/Cntr=0.5,0.3

Type RM Length L Ch R = 3 ,522.8   ,,,
BEGIN DESCRIPTION:
WILLOWICK
Cross Section 522.8
Structure ID: M109-01-00-01
END DESCRIPTION:
Bridge Culvert--1,0,-1,-1, 0
Deck Dist Width WeirC Skew NumUp NumDn MinLoCord MaxHiCord MaxSubmerge Is_Ogee
10,34,2.6,0, 60, 60, , , 0.95, 0, 1,1,,
  4543.1    4546    4556    4566    4576    4586    4616    4646    4666    4676
    4686    4696    4726    4736  4763.1    4776  4783.1    4796    4816  4821.5
  4887.4  4898.6  4950.3  4953.8 4953.87 4953.98 4954.21  4954.3  4954.4  5003.4
  5043.7 5043.81 5043.89    5044  5044.2  5110.1  5146.5  5161.4    5193  5193.1
  5241.7  5243.1    5246  5253.1    5256  5263.1  5273.1  5283.1    5296    5316
    5326    5336    5346  5356.9  5368.2  5388.2  5448.2  5466.9  5495.7  5534.4
  137.15  137.55  137.25  137.25  136.95  136.45  135.75   135.4  135.25  135.25
  135.45  135.35  134.75  134.45     134  134.29   134.5  134.65   134.4  134.83
  135.21  134.95  135.18   135.2  135.33  139.03  139.17  139.27  139.39   139.1
  139.32  135.62  135.62  135.62  135.19  134.16  133.47  133.44  133.37  132.66
  133.64  132.83  132.23   132.3  132.16   131.8   132.4   132.2  132.36  132.66
   132.8   132.8  132.77   132.7   132.8  132.75  133.75  133.94  134.05  133.75
  137.15  137.55  137.25  137.25  136.95  136.45  135.75  135.35  135.25  135.25
  135.45  135.35  134.75  134.45  133.98  134.05  134.26  134.65  134.25  134.83
  135.21  133.83   133.2   132.3  132.28  132.26   132.2  133.82  133.94  133.65
  133.87  133.87  133.87  132.03  132.08  131.91  131.99  132.02  132.66  132.66
  133.64  132.83  131.15  131.15  131.15  131.43  131.83  132.09  132.25  132.05
  132.45  131.75  131.75  132.02  132.45  132.75  133.75  133.94  134.05  133.75
  4543.1    4546    4556    4566    4576    4586    4606    4616    4646    4676
    4686    4696    4746    4766    4776    4796    4816  4821.5  4887.4  4898.6
  4950.3  4953.8 4953.87 4953.98 4954.09 4954.21  4954.3  4954.4  5003.4  5043.7
 5043.81 5043.89    5044  5044.2  5110.1  5146.5  5161.4    5193  5193.1  5241.7
  5243.1    5246  5253.1    5256  5263.1  5273.1  5283.1    5296    5316    5326
    5336    5346  5356.9  5368.2  5388.2  5428.2  5448.2  5466.9  5495.7  5534.4
  137.31  137.71  137.41  137.41  137.11  136.61  136.21  135.91  135.51  135.41
  135.61  135.51  134.41  134.11  134.29  134.81  134.41  134.99  135.37  134.95
  135.18   135.2  135.33  139.03  139.03  139.17  139.27  139.39   139.1  139.32
  135.62  135.62  135.62  135.19  134.16  133.47  133.44  133.37  132.82   133.8
  132.99  132.23   132.3  132.16   131.8   132.4  132.25  132.41  132.66   132.8
   132.8  132.77   132.7   132.8  132.91  133.51  133.91   134.1  134.21  133.91
  137.31  137.71  137.41  137.41  137.11  136.61  136.21  135.91  135.51  135.41
  135.61  135.51  134.41  134.11  134.21  134.81  134.41  134.99  135.37  133.99
  133.36  132.46  132.44  132.42  132.39  132.36  133.98   134.1  133.81  134.03
  134.03  134.03  132.19  132.24  132.07  132.15  132.18  132.82  132.82   133.8
  132.99  131.31  131.31  131.31  131.59  131.99  132.25  132.41  132.21  132.61
  131.91  131.91  132.18  132.61  132.91  133.51  133.91   134.1  134.21  133.91
Pier Skew, UpSta & Num, DnSta & Num=  ,4983.3, 2 ,4983.3, 2 , 0 , 0 , 0 ,,
     1.1     1.1
  123.73  134.77
     1.1     1.1
  123.89  134.93
Pier Skew, UpSta & Num, DnSta & Num=  ,5014.2, 2 ,5014.2, 2 , 0 , 0 , 0 ,,
     1.1     1.1
  122.12  134.71
     1.1     1.1
  122.28  134.87
Abutment Skew #Up #Dn= , 2 , 2
  4954.1  4978.8
  133.82  125.89
  4954.1  4978.8
  133.98  126.05
Abutment Skew #Up #Dn= , 2 , 2
  5018.6 5044.09
  125.97  133.87
  5018.6 5044.09
  126.13  134.03
BR Coef= 1 , 1 , 1 ,1.25, 0 ,,,0.8,0,2,0,
WSPro=,,,, 1 ,,,, 0 ,,,, 0 ,,,,-1 ,-1 ,-1 , 0 , 0 , 0 , 0 , 0
BR U #Sta/Elev= 151
  4543.1  137.15    4546  137.55  4553.1  137.34    4556  137.25  4563.1  137.25
    4566  137.25  4573.1  137.04    4576  136.95  4583.1   136.6    4586  136.45
  4593.1  136.31    4596  136.25  4603.1  136.11    4606  136.05    4616  135.75
  4623.1  135.64  4633.1  135.49    4636  135.45    4646  135.35  4653.1  135.35
    4656  135.35  4663.1  135.28    4666  135.25  4673.1  135.25    4676  135.25
  4683.1  135.39    4686  135.45  4693.1  135.38    4696  135.35  4703.1  135.21
    4706  135.15  4713.1  135.01    4716  134.95  4723.1  134.81    4726  134.75
  4733.1  134.54    4736  134.45    4746  134.25  4753.1  134.11    4756  134.05
  4763.1  133.98    4766  133.95  4773.1  134.02    4776  134.05  4783.1  134.26
    4786  134.35    4796  134.65  4803.1  134.51  4813.1  134.31    4816  134.25
  4821.5  134.83  4833.1   134.9  4843.1  134.95  4853.1  135.01  4870.5  135.11
  4887.4  135.21  4898.6  133.83  4917.6   133.6  4950.3   133.2  4953.8   132.3
 4953.87  132.28 4953.98  132.26 4954.09  132.23 4954.21   132.2  4954.3  132.17
  4954.4  132.15  4978.7  125.92  4978.8  125.89  4983.3  124.73  4994.5  124.72
  4998.3  122.16  4999.2  121.73  5000.5  121.12  5001.4  121.58  5001.7  122.26
  5003.4  122.38  5014.2  123.16  5018.5  125.91  5018.6  125.97 5043.59  131.94
  5043.7  131.96 5043.81  131.99 5043.89  132.01    5044  132.03  5044.1  132.06
  5044.2  132.08  5044.4  132.13  5099.8  131.94  5110.1  131.91  5146.5  131.99
  5161.3  132.02  5161.4  132.02    5193  132.66  5193.1  132.66  5203.1  132.86
  5213.1  133.06  5223.1  133.26  5233.1  133.47  5241.7  133.64  5243.1  132.83
    5246  131.15  5253.1  131.15    5256  131.15  5263.1  131.43  5273.1  131.83
    5276  131.95  5283.1  132.09    5286  132.15  5293.1  132.22    5296  132.25
  5303.1  132.18  5313.1  132.08    5316  132.05  5323.1  132.33    5326  132.45
  5333.1  131.95    5336  131.75  5343.1  131.75    5346  131.75  5348.2  131.85
  5353.1  131.95  5356.9  132.02  5358.2  132.05  5366.9   132.4  5368.2  132.45
  5376.9  132.62  5378.2  132.65  5386.9  132.74  5388.2  132.75  5396.9  132.92
  5398.2  132.95  5406.9  133.07  5416.9   133.2  5426.9  133.33  5428.2  133.35
  5436.9  133.52  5438.2  133.55  5446.9  133.72  5448.2  133.75  5456.9  133.84
  5458.2  133.85  5466.9  133.94  5468.2  133.95  5476.9  133.99  5486.9  134.04
  5488.2  134.05  5495.7  134.05  5496.9  134.04  5506.9  133.96  5516.9  133.89
  5534.4  133.75
BR U #Mann= 3
  4543.1     .12  4950.3     .03  5044.4     .12
BR U Banks=4950.3,5044.4
BR D #Sta/Elev= 151
  4543.1  137.31    4546  137.71  4553.1   137.5    4556  137.41  4563.1  137.41
    4566  137.41  4573.1   137.2    4576  137.11  4583.1  136.76    4586  136.61
  4593.1  136.47    4596  136.41  4603.1  136.27    4606  136.21    4616  135.91
  4623.1   135.8  4633.1  135.65    4636  135.61    4646  135.51  4653.1  135.51
    4656  135.51  4663.1  135.44    4666  135.41  4673.1  135.41    4676  135.41
  4683.1  135.55    4686  135.61  4693.1  135.54    4696  135.51  4703.1  135.37
    4706  135.31  4713.1  135.17    4716  135.11  4723.1  134.97    4726  134.91
  4733.1   134.7    4736  134.61    4746  134.41  4753.1  134.27    4756  134.21
  4763.1  134.14    4766  134.11  4773.1  134.18    4776  134.21  4783.1  134.42
    4786  134.51    4796  134.81  4803.1  134.67  4813.1  134.47    4816  134.41
  4821.5  134.99  4833.1  135.06  4843.1  135.11  4853.1  135.17  4870.5  135.27
  4887.4  135.37  4898.6  133.99  4917.6  133.76  4950.3  133.36  4953.8  132.46
 4953.87  132.44 4953.98  132.42 4954.09  132.39 4954.21  132.36  4954.3  132.33
  4954.4  132.31  4978.7  126.08  4978.8  126.05  4983.3  124.89  4994.5  124.88
  4998.3  122.32  4999.2  121.89  5000.5  121.28  5001.4  121.74  5001.7  122.42
  5003.4  122.54  5014.2  123.32  5018.5  126.07  5018.6  126.13 5043.59   132.1
  5043.7  132.12 5043.81  132.15 5043.89  132.17    5044  132.19  5044.1  132.22
  5044.2  132.24  5044.4  132.29  5099.8   132.1  5110.1  132.07  5146.5  132.15
  5161.3  132.18  5161.4  132.18    5193  132.82  5193.1  132.82  5203.1  133.02
  5213.1  133.22  5223.1  133.42  5233.1  133.63  5241.7   133.8  5243.1  132.99
    5246  131.31  5253.1  131.31    5256  131.31  5263.1  131.59  5273.1  131.99
    5276  132.11  5283.1  132.25    5286  132.31  5293.1  132.38    5296  132.41
  5303.1  132.34  5313.1  132.24    5316  132.21  5323.1  132.49    5326  132.61
  5333.1  132.11    5336  131.91  5343.1  131.91    5346  131.91  5348.2  132.01
  5353.1  132.11  5356.9  132.18  5358.2  132.21  5366.9  132.56  5368.2  132.61
  5376.9  132.78  5378.2  132.81  5386.9   132.9  5388.2  132.91  5396.9  133.08
  5398.2  133.11  5406.9  133.23  5416.9  133.36  5426.9  133.49  5428.2  133.51
  5436.9  133.68  5438.2  133.71  5446.9  133.88  5448.2  133.91  5456.9     134
  5458.2  134.01  5466.9   134.1  5468.2  134.11  5476.9  134.15  5486.9   134.2
  5488.2  134.21  5495.7  134.21  5496.9   134.2  5506.9  134.12  5516.9  134.05
  5534.4  133.91
BR D #Mann= 3
  4543.1     .12  4950.3     .03  5044.4     .12
BR D Banks=4950.3,5044.4
BC Design=,, 0 ,, 0 ,,,,,,
BC HTab HWMax=137.5

Type RM Length L Ch R = 1 ,495.8   ,90.8,90.8,90.8
BEGIN DESCRIPTION:
Downstream Section of Bridge/Culvert/Weir
END DESCRIPTION:
XS GIS Cut Line= 3
      3060104.67      13970474.1      3059462.01      13969974.8
      3059288.98      13970014.3
#Sta/Elev= 30
  4543.1  137.36    4546  137.76    4566  137.46    4586  136.66    4616  135.96
    4646  135.56    4696  135.56    4766  134.16    4796  134.86  4950.3  133.41
  4983.3  124.94  4994.5  124.93  4998.3  122.37  5000.5  121.33  5001.4  121.79
  5001.7  122.47  5014.2  123.37  5018.6  126.18  5044.4  132.34  5161.4  132.23
    5256  131.36    5286  132.36    5316  132.26    5326  132.66    5336  131.96
    5346  131.96  5378.2  132.86  5466.9  134.15  5495.7  134.26  5534.4  133.96
#Mann= 4 ,-1 , 0
  4543.1     .12       0  4950.3     .04       0  5044.4     .12       0
  5534.4      .2       0
#XS Ineff= 2 , 0
       0  4950.3  133.41  5044.4       0   132.5
Permanent Ineff=
       F       F
Bank Sta=4950.3,5044.4
Exp/Cntr=0.5,0.3

Type RM Length L Ch R = 1 ,405.0   ,0,0,0
BEGIN DESCRIPTION:
Cross Section 405
Cross Section XS01-Bridge1-exp
END DESCRIPTION:
XS GIS Cut Line= 4
      3060151.18      13970435.8      3059795.24      13970119.4
      3059478.85      13969911.8       3059179.2      13969986.2
#Sta/Elev= 30
  4535.4   136.5  4595.4   136.2  4635.4   135.3  4675.4   136.5  4735.4   133.7
  4765.4   132.9  4785.4   133.8  4815.4   132.8  4835.4   133.4  4895.4   133.2
 4901.25  133.78 4952.95  133.15 4985.95  124.68 4997.15  124.67 5003.15  121.07
 5004.05  121.53 5007.35  125.38 5016.85  123.11 5021.25  125.92 5047.05  132.08
 5163.95  131.97  5191.6     131  5291.6   132.3  5361.6   131.9  5381.6   132.4
  5450.1   132.2  5520.1   132.8  5560.1   131.9  5630.1   132.4  5698.8   133.9
#Mann= 5 , 1 , 0
  4535.4      .2       0  4535.4     .12       0 4952.95     .04       0
 5047.05     .12       0  5698.8      .2       0
Bank Sta=4952.95,5047.05
Exp/Cntr=0.3,0.1

Chan Stop Cuts=-1
Use User Specified Reach Order=0
User Specified Reach Order=M109-01-00      ,Reach - 1